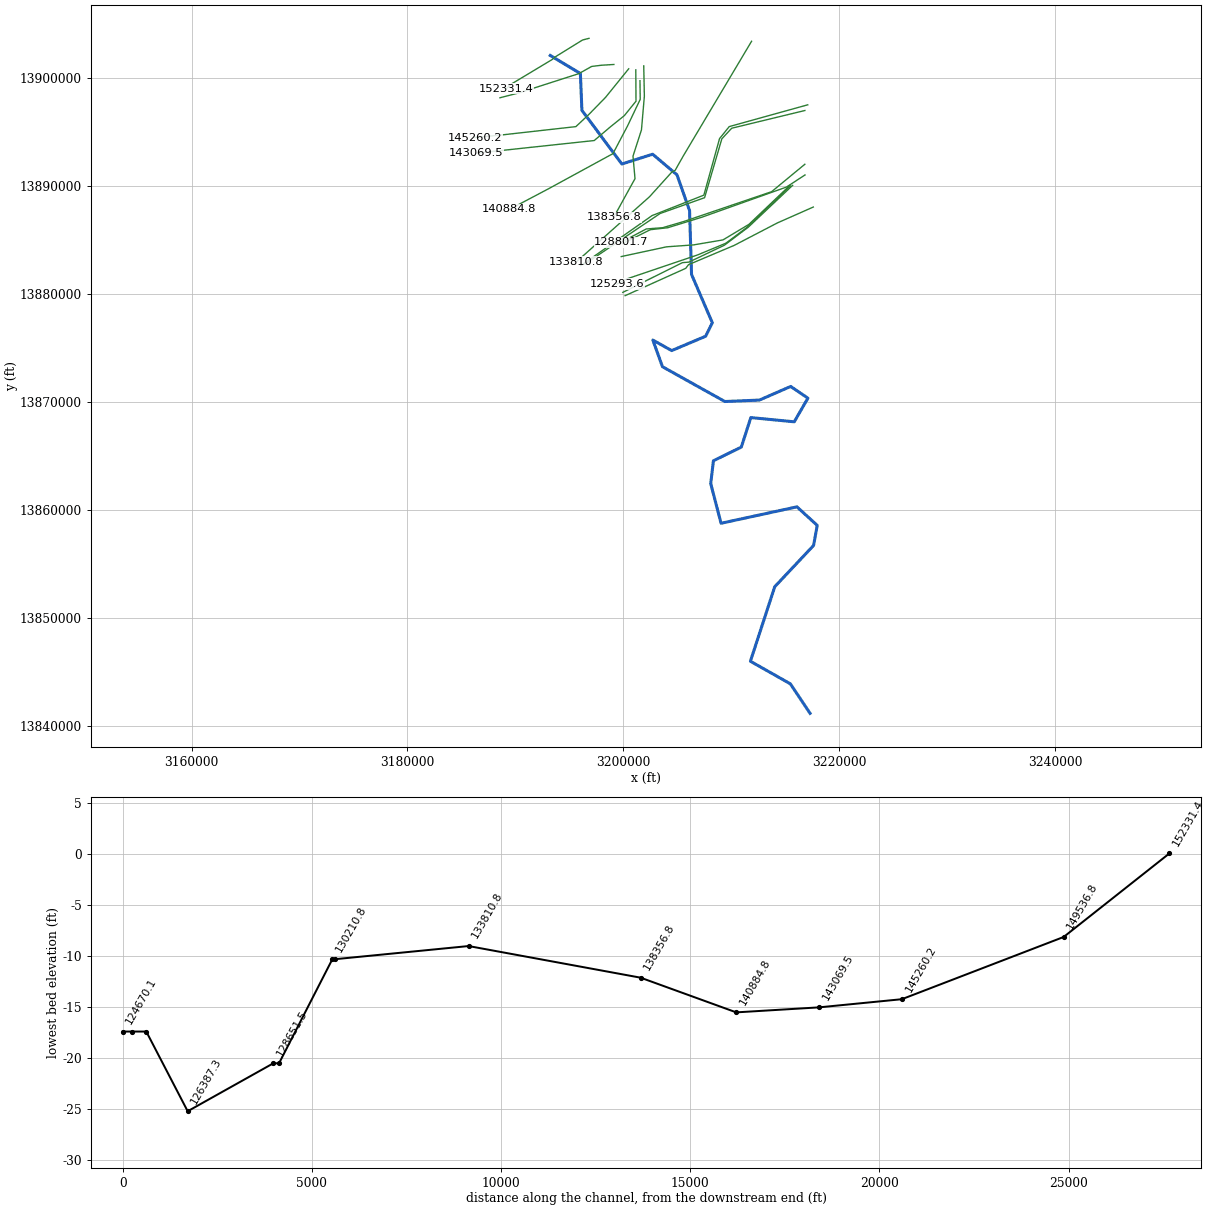
--- G103-00-00.prj (project) ---

Proj Title=G103-00-00SJ
Current Plan=p02
Default Exp/Contr=.3,.1
English Units
Geom File=g01
Flow File=f01
Flow File=f02
Plan File=p01
Plan File=p02
Y Axis Title=Elevation
X Axis Title(PF)=Main Channel Distance
X Axis Title(XS)=Station
BEGIN DESCRIPTION:
San Jacinto River Watershed  Correccted/Revised by LAN LOMR JAN2020
San Jacinto River
HCFCD unit G103-00-00
(Flood Hazard, Floodway)Model
10, 2, 1, 0.2% Event
Filename G1030000.prj
Prepared by:  FTN Associates Ltd.   DATE:  February 2003
Reviewed by:     DATE:
STATUS (Final)
Normal Depth Slope Calculated between RS 72968.31 and RS 62987.20 with inverts -23.08 and -28.77 respectively. Distance between cross sections is 9981.11. Normal depth slope calculated to be 0.00057.
The Discharge decreases downstream as per the effective FIS HEC-2 model
END DESCRIPTION:
DSS Export Rating Curves= 0
DSS Export Rating Curve Sorted= 0
DSS Export Volume Flow Curves= 0
DXF OffsetX= 0
DXF OffsetY= 0
DXF ScaleX= 1
DXF ScaleY= 10

--- G103-00-00.p02 (plan) ---

Plan Title=FEMA Effective June 2007
Version=Version 3.0.1  May 2012
Short Identifier=FEMAeff0607
Geom File=g01
Flow File=f02
Subcritical Flow
K Sum by GR= 0
Std Step Tol= 0.003
Critical Tol= 0.003
Num of Std Step Trials= 20
Max Error Tol= 0.1
Flow Tol Ratio= 0.001
Split Flow NTrial= 30
Split Flow Tol= 0.02
Split Flow Ratio= 0.02
Log Output Level= 0
Friction Slope Method= 1
Unsteady Friction Slope Method= 2
Parabolic Critical Depth
Global Vel Dist= 0 , 0 , 0
Global Log Level= 0
CheckData=True
Encroach Param=-1 ,0,0, 2
BEGIN DESCRIPTION:
FEMA Effective Multi-Profile 2007 + LOMR 20-06-2019P
END DESCRIPTION:
Computation Interval=1HOUR
Output Interval=1HOUR
Run HTab= 0
Run UNet= 0
Run PostProcess= 0
UNET Theta= 1
UNET ZTol= 0.02
UNET ZSATol= 0.1
UNET MxIter= 20
UNET MaxInSteps= 20
UNET DtIC= 0
UNET DtMin= 0
UNET MaxCRTS= 20
UNET WFStab= 2
UNET SFStab= 1
UNET WFX= 1
UNET SFX= 1
UNET Convert EG Bridges=-1
UNET Use Existing IB Tables=-1
Instantaneous Interval=1HOUR
DSS File=dss
Write IC File= 0
Write Velocity= 0
Write Detailed= 0

--- G103-00-00.p01 (plan) ---

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Plan Title=Effective Floodway 2020
Short Identifier=Eff_Floodway
Geom File=g01
Flow File=f01
Encroach River=G103-00-00SJ
Encroach Reach=G1030000SJ_0630
Encroach Node=152331.4
       1    1508    6168
Encroach Node=149536.8
       1    2609    7441
Encroach Node=145260.2
       1    4425   12692
Encroach Node=143069.5
       1    4468   15611
Encroach Node=140884.8
       1    3325   13628
Encroach Node=138356.8
       1    4413 9250.13
Encroach Node=133810.8
       1    8286   16049
Encroach Node=130278.1
       1   12923   17705
Encroach Node=130244
       1   12923   17705
Encroach Node=130210.8
       1   12850   17797
Encroach Node=128801.7
       1    4865   12648
Encroach Node=128727
       1    4866   12624
Encroach Node=128651.5
       1    4866   12624
Encroach Node=126387.3
       1    4534   12267
Encroach Node=125293.6
       1    6493   13894
Encroach Node=124916.8
       1    7181   14724
Encroach Node=124793
       1    7181   14724
Encroach Node=124670.1
       1    7622   14942
Encroach Node=124307.5
       1    8539   15972
Encroach Node=120765.0
       1    7315   16009
Encroach Node=115185.6
       1    5356   14337
Encroach Node=107787.5
       1    5323   15757
Encroach Node=104366.2
       1    2453   10346
Encroach Node=101780.6
       1    1700    9703
Encroach Node=97516.01
       1    3900   13331
Encroach Node=94463.95
       1 4906.6415862.02
Encroach Node=93063.22
       1 3350.39   14308
Encroach Node=86250.95
       1  1479.3    5375
Encroach Node=83974.91
       1 3550.93    8530
Encroach Node=79907.59
       1    2264 7596.89
Encroach Node=75450.01
       1 4369.81 8741.81
Encroach Node=75388
       1 4369.81 8741.81
Encroach Node=75326.78
       1 4369.81 8741.81
Encroach Node=72968.31
       1 1862.13    9313
Encroach Node=67924.46
       1  624.13    6566
Encroach Node=65261.75
       1   990.9    8300
Encroach Node=62987.20
       1  702.23    7800
Effective floodway updated by FEMA LOMR case 20-06-2019P
IC Time=0

--- G103-00-00.f02 (steady flow) ---

Flow Title=FEMA Effective June 2007
Version=Version 3.0.1  Mar 2001
Number of Profiles= 4
Profile Names=10PCT_10yr, 2PCT_50yr, 1PCT_100yr, 0.2PCT_500yr
River Rch & RM=G103-00-00SJ,G1030000SJ_0630     ,152331.4
   82268  180481  246067  409602
River Rch & RM=G103-00-00SJ,G1030000SJ_0630     ,143069.5
   82141  178832  246035  409317
River Rch & RM=G103-00-00SJ,G1030000SJ_0630     ,133810.8
   85000  183000  254000  422000
River Rch & RM=G103-00-00SJ,G1030000SJ_0630     ,128801.7
   84952  182952  253952  421952
River Rch & RM=G103-00-00SJ,G1030000SJ_0630     ,126387.3
   84556  182556  253556  421556
River Rch & RM=G103-00-00SJ,G1030000SJ_0630     ,107787.5
   84161  182161  253161  421161
River Rch & RM=G103-00-00SJ,G1030000SJ_0630     ,97516.01
   83915  181915  252915  420915
River Rch & RM=G103-00-00SJ,G1030000SJ_0630     ,86250.95
   83654  181654  252654  420654
River Rch & RM=G103-00-00SJ,G1030000SJ_0630     ,79907.59
   83412  181412  252412  420412
River Rch & RM=G103-00-00SJ,G1030000SJ_0630     ,72968.31
   83185  181185  252185  420185
River Rch & RM=G103-00-00SJ,G1030000SJ_0630     ,65261.75
   83000  181000  252000  418968
Boundary for River Rch & Prof#=G103-00-00SJ,G1030000SJ_0630     , 1
Up Type= 0
Dn Type= 3
Dn Slope=.00057
Boundary for River Rch & Prof#=G103-00-00SJ,G1030000SJ_0630     , 2
Up Type= 0
Dn Type= 3
Dn Slope=.00057
Boundary for River Rch & Prof#=G103-00-00SJ,G1030000SJ_0630     , 3
Up Type= 0
Dn Type= 3
Dn Slope=.00057
Boundary for River Rch & Prof#=G103-00-00SJ,G1030000SJ_0630     , 4
Up Type= 0
Dn Type= 3
Dn Slope=.00057
DSS Import GetInterval= 0
DSS Import GetPeak= 0
DSS Import FillOption= 0

--- G103-00-00.f01 (steady flow) ---

Flow Title=Floodway
Version=Version 3.0.1  Mar 2001
Number of Profiles= 2
Profile Names=1PCT_100yr, 1PCTFloodway_100yrFW
River Rch & RM=G103-00-00SJ,G1030000SJ_0630      ,152331.4
  246067  246067
River Rch & RM=G103-00-00SJ,G1030000SJ_0630      ,143069.5
  246035  246035
River Rch & RM=G103-00-00SJ,G1030000SJ_0630      ,133810.8
  254000  254000
River Rch & RM=G103-00-00SJ,G1030000SJ_0630      ,128801.7
  253952  253952
River Rch & RM=G103-00-00SJ,G1030000SJ_0630      ,126387.3
  253556  253556
River Rch & RM=G103-00-00SJ,G1030000SJ_0630      ,107787.5
  253161  253161
River Rch & RM=G103-00-00SJ,G1030000SJ_0630      ,97516.01
  252915  252915
River Rch & RM=G103-00-00SJ,G1030000SJ_0630      ,86250.95
  252654  252654
River Rch & RM=G103-00-00SJ,G1030000SJ_0630      ,79907.59
  252412  252412
River Rch & RM=G103-00-00SJ,G1030000SJ_0630      ,72968.31
  252185  252185
River Rch & RM=G103-00-00SJ,G1030000SJ_0630      ,65261.75
  252000  252000
Boundary for River Rch & Prof#=G103-00-00SJ,G1030000SJ_0630      , 1
Up Type= 0
Dn Type= 3
Dn Slope=.00057
Boundary for River Rch & Prof#=G103-00-00SJ,G1030000SJ_0630      , 2
Up Type= 0
Dn Type= 3
Dn Slope=.00057
DSS Import GetInterval= 0
DSS Import GetPeak= 0
DSS Import FillOption= 0

--- G103-00-00.g01 (geometry) ---

Geom Title=G103-00-00SJ June 2007
Version=Version 3.0.1  May 2012

River Reach=G103-00-00SJ    ,G1030000SJ_0630
Reach XY= 30
        3193225.       13902106.      3196013.75       13900433.
        3196155.       13897022.        3199853.       13892054.
      3202708.25       13892961.        3204960.       13891052.
        3206126.       13887736.      3206308.25       13881828.
      3208232.75       13877355.      3207613.25       13876102.
      3204468.75       13874773.       3202724.5       13875749.
      3203617.75       13873278.       3209394.5       13870057.
       3212593.5       13870189.       3215491.5       13871452.
      3217085.25       13870366.       3215821.5       13868178.
       3211798.5       13868568.       3210917.5       13865834.
        3208335.       13864568.        3208085.       13862455.
      3209042.25       13858780.        3216071.       13860301.
        3217949.       13858586.      3217610.75       13856725.
      3214014.75       13852904.      3211761.25       13846000.
      3215459.25       13843910.     3217287.104    13841173.419

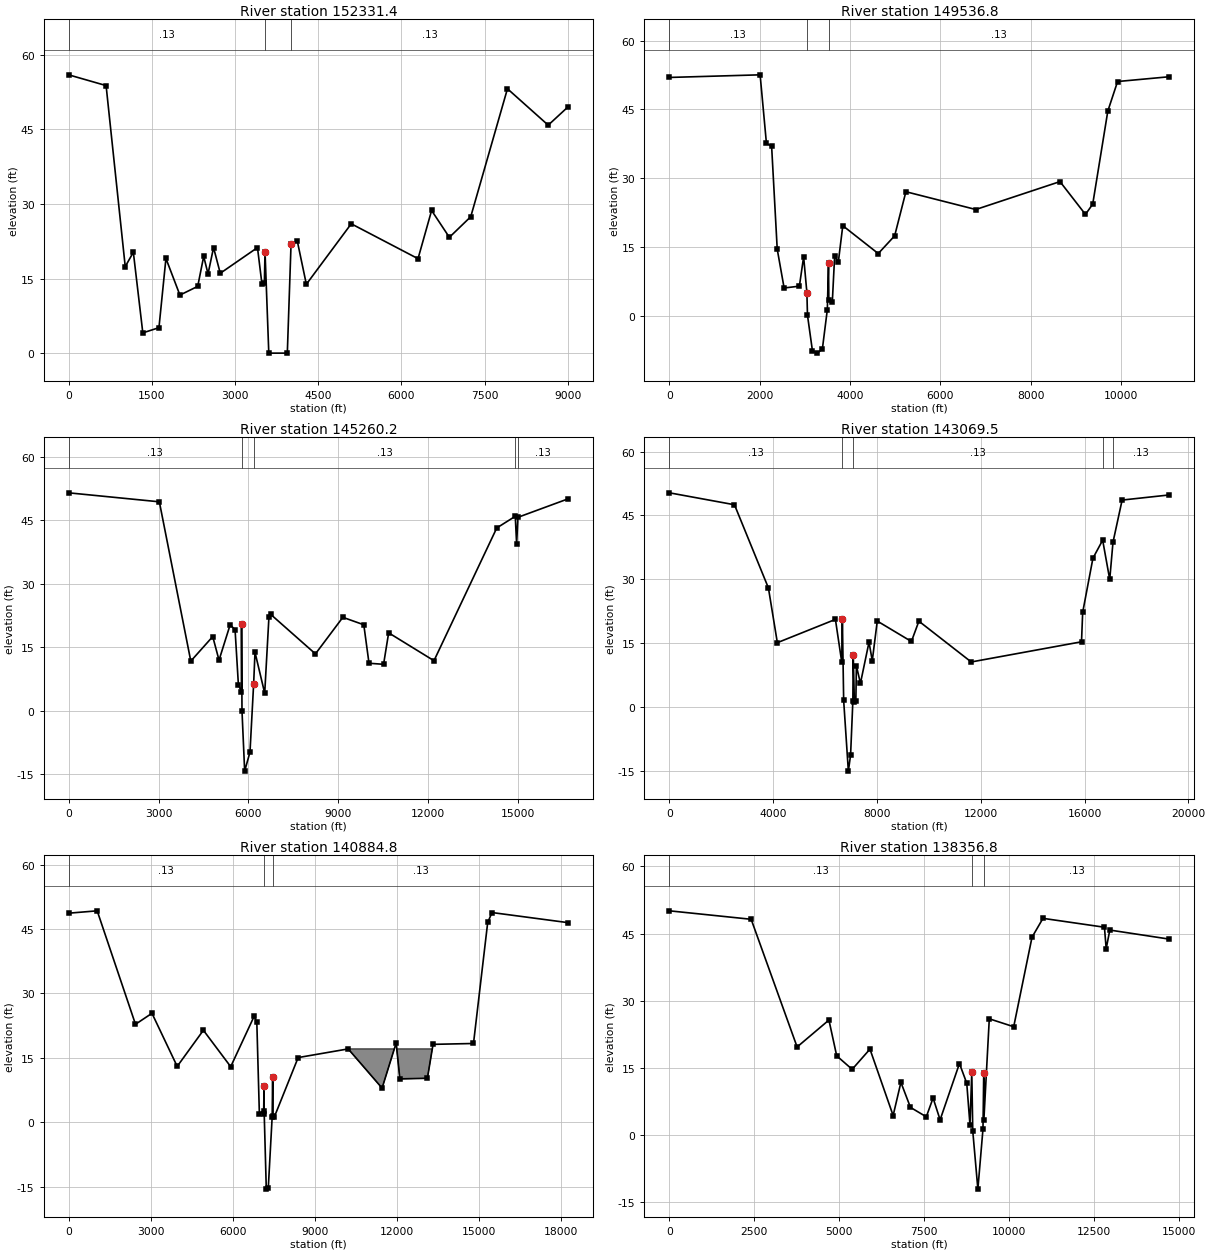
Type RM Length L Ch R = 1 ,152331.4,2675.56,2794.6,2474.37
BEGIN DESCRIPTION:
sj28p83
Bank Station offset =     19377
---- FLOW CHANGE LOCATION
END DESCRIPTION:
XS GIS Cut Line= 6
     3196813.781    13903692.437     3196214.044    13903537.666
     3193679.671    13901970.611     3193396.492    13901729.075
     3189670.776    13899488.446     3189152.624    13899029.965
#Sta/Elev= 30
       0   55.94  675.26   53.78 1020.42   17.42 1166.72    20.3 1337.54    4.11
 1628.47    5.15 1754.33   19.06 2006.42    11.7 2327.52   13.45  2435.3   19.47
 2513.67   15.95 2613.02   21.24 2734.27   16.08 3405.36   21.24 3485.95   13.91
 3529.78    14.2 3541.39   20.45 3609.39     .04 3943.39     .04 4010.39   21.87
 4123.68   22.54 4286.67   13.87 5096.22   26.02 6300.64   19.01  6545.5   28.69
 6865.82    23.3 7251.33   27.44 7913.28   53.14 8648.42   45.83 9011.18   49.56
#Mann= 3 , 0 , 0
       0     .13       0 3541.39     .03       0 4010.39     .13       0
Bank Sta=3541.39,4010.39
XS Rating Curve= 0
Exp/Cntr=.3,.1

Type RM Length L Ch R = 1 ,149536.8,3833.33,4276.55,4829.86
BEGIN DESCRIPTION:
sj28p29
Bank Station offset =     19264
Low area on the ROB is a small side channel, overtopped - hence not made ineffective
END DESCRIPTION:
XS GIS Cut Line= 6
     3199114.183    13901271.724     3197963.195    13901199.996
     3197058.633    13901090.352     3195879.714    13900425.321
     3190290.716    13898630.717     3188564.373    13898188.398
#Sta/Elev= 30
       0   51.99 2008.46   52.56 2148.21   37.62 2263.38   36.97 2387.37   14.53
 2540.14    6.06 2878.68    6.46 2972.58   12.86 3044.85    5.05 3057.85     .12
 3167.85   -7.65 3277.85   -8.15 3387.85   -7.25 3497.85    1.35 3523.85   11.45
 3531.11    3.52 3608.17    2.99 3659.94   13.08 3740.75   11.67 3840.25   19.65
 4625.92   13.57 4989.58   17.44 5238.65   27.06 6787.89   23.18 8652.98   29.27
 9217.35   22.11 9378.31   24.35 9712.96   44.65 9929.24    51.111072.16   52.14
#Mann= 3 , 0 , 0
       0     .13       0 3044.85     .03       0 3523.85     .13       0
Bank Sta=3044.85,3523.85
XS Rating Curve= 0
Exp/Cntr=.3,.1

Type RM Length L Ch R = 1 ,145260.2,2570.11,2190.78,1501.39
BEGIN DESCRIPTION:
sj27p445
Bank Station offset =     19026
---- FLOW CHANGE LOCATION
Low area on the LOB is a ponding as seen from the MrSids, hence blocked.
END DESCRIPTION:
XS GIS Cut Line= 6
     3200487.707     13900871.15     3198339.242    13898219.441
     3196779.323    13896622.338     3195596.761    13895515.375
     3188816.316      13894754.8      3186242.03    13894503.178
#Sta/Elev= 30
       0   51.43 3026.82   49.31 4076.28   11.71  4808.4   17.51 5018.27   11.94
 5390.32   20.31 5553.84    19.1 5664.62    6.15 5766.92    4.49 5769.64   20.55
 5784.64    -.01 5873.64  -14.25 6051.64   -9.75 6173.64    6.35 6218.83    13.8
 6542.81    4.13 6683.87   22.11 6745.54   22.73 8235.88   13.42  9150.7   22.05
 9849.76   20.2910023.34   11.2110509.75   10.96   10679   18.3912191.81   11.81
14286.91   43.1414904.73   45.8914949.92   39.3314992.97   45.6516675.26   50.03
#Mann= 5 ,-1 , 0
       0     .13       0 5769.64     .03       0 6173.64     .13       0
14904.73     .99       014992.97     .13       0
Bank Sta=5769.64,6173.64
XS Rating Curve= 0
Exp/Cntr=.3,.1

Type RM Length L Ch R = 1 ,143069.5,1010.63,2184.69,2841.51
BEGIN DESCRIPTION:
sj27p00
Bank Station offset =     18258
END DESCRIPTION:
XS GIS Cut Line= 6
     3201145.795    13900774.373     3201165.151    13897871.042
     3200081.859    13896531.552     3198836.209    13895529.349
     3197296.375    13894226.828     3186338.807    13893051.512
#Sta/Elev= 30
       0   50.32 2505.37   47.52 3814.25   27.97 4158.13   15.12 6396.91   20.59
 6639.77   10.61 6664.89   20.75 6714.89    1.55 6895.89  -15.05 6981.89  -11.25
 7068.89    1.35 7083.89   12.15  7127.2    1.27 7184.43    1.33  7205.7    9.68
 7361.18    5.57 7692.35   15.25 7817.77   10.88 8009.89    20.2 9326.29    15.4
 9614.68   20.1711632.56   10.5915883.53   15.3315928.84   22.2416324.07   34.96
16699.32    39.216971.62   29.9717097.19   38.7117449.49   48.6219262.69   49.82
#Mann= 5 ,-1 , 0
       0     .13       0 6664.89     .03       0 7083.89     .13       0
16699.32     .99       017097.19     .13       0
Bank Sta=6664.89,7083.89
XS Rating Curve= 0
Exp/Cntr=.3,.1

Type RM Length L Ch R = 1 ,140884.8,1124.15,2528.02,4267.81
BEGIN DESCRIPTION:
sj26p60
Bank Station offset =     18278
Low area on ROB is ponding as seen from the MrSids, hence blocked
END DESCRIPTION:
XS GIS Cut Line= 6
     3201532.906    13899767.884     3201554.854    13898040.114
     3200379.293    13895575.117      3199029.67    13893012.481
      3193017.42    13889735.958     3189435.694    13887844.872
#Sta/Elev= 30
       0   48.69 1042.31   49.24  2441.5   22.83 3043.31   25.39  3965.3   13.03
 4921.87   21.44  5919.8   12.96 6774.71   24.68 6873.49   23.33    6967    2.02
 7125.17    2.74 7136.97    8.46 7143.97    1.96 7219.97  -15.54 7291.97  -15.34
 7434.97    1.36 7452.97   10.66 7465.53    1.37 7506.77    1.15 8383.48   15.08
10211.64    17.111449.77    7.9711964.05   18.49 12098.4   10.1213104.64   10.26
13311.27   18.1614788.61   18.36 15307.9   46.5415466.04   48.8418253.13   46.48
#Mann= 3 , 0 , 0
       0     .13       0 7136.97     .03       0 7452.97     .13       0
#Block Obstruct= 1 ,-1
10211.6413413.47    17.1
Bank Sta=7136.97,7452.97
XS Rating Curve= 0
Exp/Cntr=.3,.1

Type RM Length L Ch R = 1 ,138356.8,5196.45,4545.94,3229.59
BEGIN DESCRIPTION:
sj26p06
Bank Station offset =     17376
---- FLOW CHANGE LOCATION
END DESCRIPTION:
XS GIS Cut Line= 6
     3201881.305    13901142.128     3201939.372    13898335.575
     3201670.863    13895214.976     3200886.123    13892779.236
     3201072.618     13890696.29     3199094.108    13887109.362
#Sta/Elev= 30
       0   50.08 2403.85   48.19 3756.46   19.64 4692.58   25.66 4921.65   17.66
 5376.11   14.64 5900.19   19.16 6582.21    4.32 6811.34   11.73 7091.43    6.14
 7558.43    4.03  7757.9    8.23 7964.82    3.35 8534.26   15.94 8748.86   11.54
 8843.67    2.24 8897.13   13.96 8926.13     .83 9076.13  -12.14 9226.13    1.26
 9250.13   13.76 9252.78    3.35 9412.41   25.9410130.67   24.1710669.77   44.18
 10992.4    48.412801.14   46.4112852.62   41.6212959.44   45.7814705.99   43.76
#Mann= 3 , 0 , 0
       0     .13       0 8897.13     .03       0 9250.13     .13       0
Bank Sta=8897.13,9250.13
XS Rating Curve= 0
Exp/Cntr=.3,.1

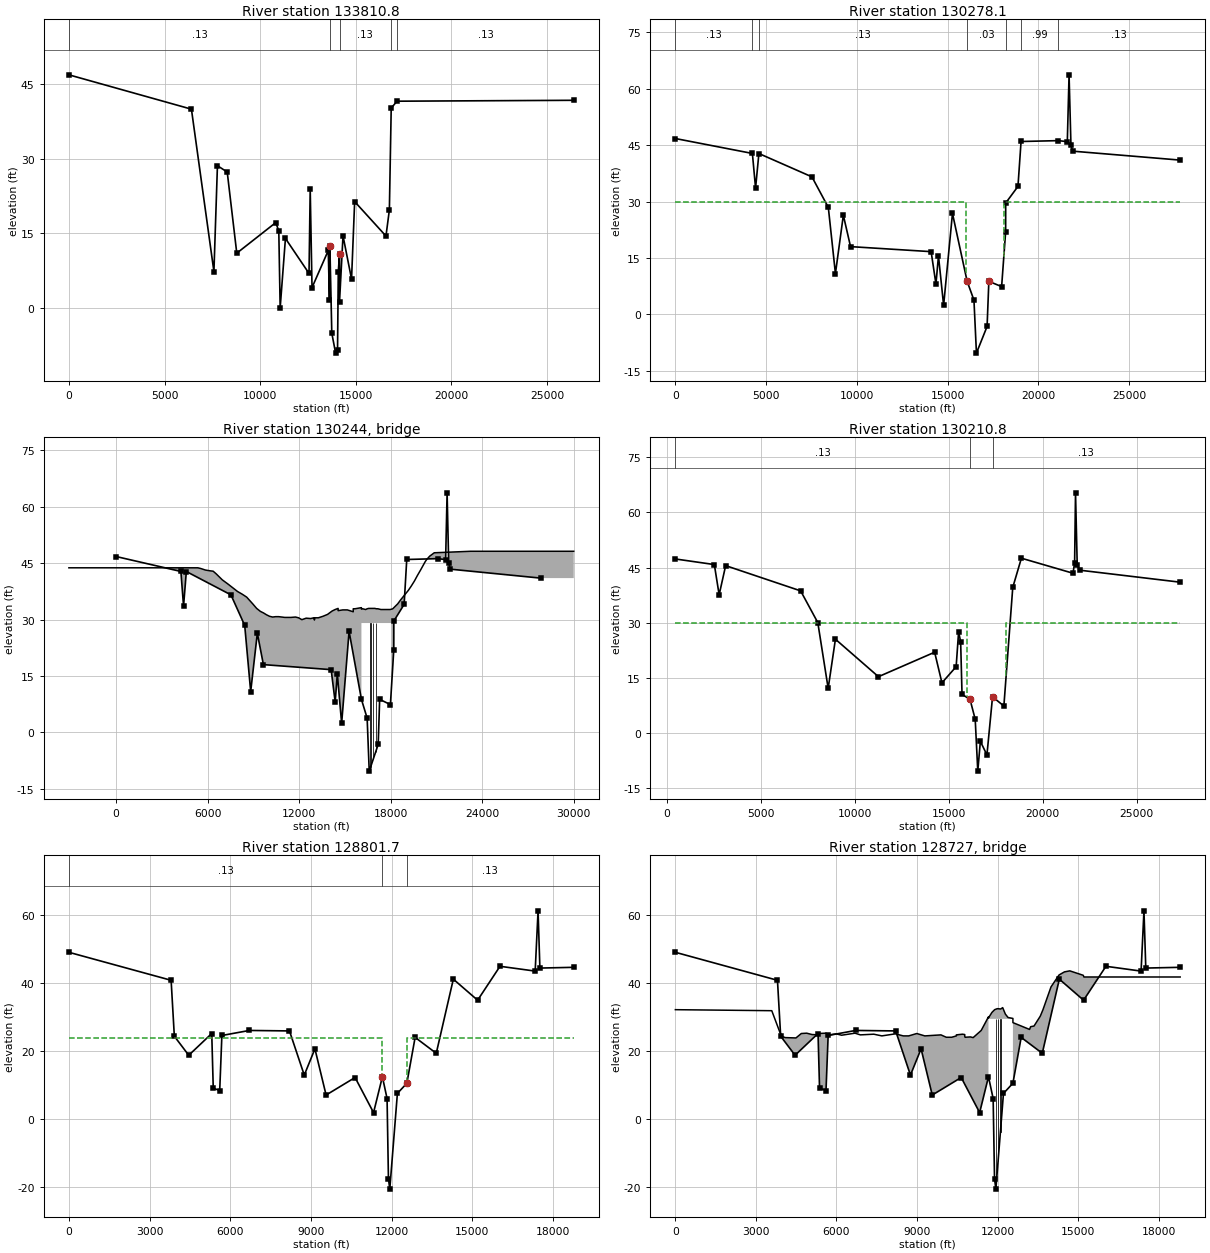
Type RM Length L Ch R = 1 ,133810.8,4206.78,3532.76,2604.71
BEGIN DESCRIPTION:
sj25p17, Xsec 4/4 of South pacific Railroad
Bank Station offset =     16254
END DESCRIPTION:
XS GIS Cut Line= 6
     3211867.264    13903418.889     3205557.345     13892822.19
     3204784.343    13891456.543     3204521.362    13891349.515
     3202412.653     13889016.28     3195641.076    13882992.462
#Sta/Elev= 30
       0   46.79 6406.27    39.9 7582.17    7.32  7766.2   28.56 8277.68   27.29
 8777.36   11.0110816.56   17.1510974.51   15.4611046.09     .04 11321.7   13.97
12554.75    6.9512616.78   23.8812711.86     4.113560.98   11.5513622.08    1.64
13645.95   12.3613745.95   -5.0413945.95   -9.0414045.95   -8.4414084.95    7.26
14148.95   10.7614149.81    1.3114332.09   14.4914778.04    5.8214940.76   21.36
16577.95   14.4516756.37   19.6916852.32   40.1217157.08    41.526394.49   41.68
#Mann= 5 ,-1 , 0
       0     .13       013645.95     .03       014148.95     .13       0
16852.32     .99       017157.08     .13       0
Bank Sta=13645.95,14148.95
XS Rating Curve= 0
Exp/Cntr=.5,.3

Type RM Length L Ch R = 1 ,130278.1,239.91,67.28,98.86
BEGIN DESCRIPTION:
sj24p513, Xsec 3/4 of South Pacific Railroad
LOB and RB reach lengths > channel reach length due to the shape of the d/s xscutline.
Bank Station offset =     14896
END DESCRIPTION:
XS GIS Cut Line= 6
     3217072.179    13897535.333     3209797.674    13895517.653
     3208900.574    13894401.388     3207448.944    13889169.508
     3202648.629    13887273.404     3196056.342     13882646.37
#Sta/Elev= 30
       0   46.77 4244.83    42.8 4420.09   33.59 4603.26   42.78 7526.86   36.57
 8429.82   28.44 8821.91   10.83 9257.83   26.36 9654.83   18.0114096.33   16.67
14361.53    8.05 14501.7   15.5314784.98    2.38 15272.9   26.8416081.92    8.77
16456.92    3.7716593.92  -10.3317180.92   -3.2317277.92    8.7717981.92    7.37
18203.92   21.9718206.99   29.6118882.54   34.0319053.52   45.98 21111.1   46.21
21603.12   45.9421699.02   63.7221803.08   45.05 21898.2   43.41 27823.4   41.03
#Mann= 7 ,-1 , 0
       0     .13       0 4244.83     .99       0 4603.26     .13       0
16081.92     .03       018203.92     .13       019053.52     .99       0
 21111.1     .13       0
#XS Ineff= 2 , 0
       0   16000   29.87   18100       0   29.87
Permanent Ineff=
       F       F
Bank Sta=16081.92,17277.92
XS Rating Curve= 0
Exp/Cntr=.5,.3

Type RM Length L Ch R = 3 ,130244  ,,,
BEGIN DESCRIPTION:
Southern Pacific RR
END DESCRIPTION:
Bridge Culvert--1,0,-1,-1, 0
Deck Dist Width WeirC Skew NumUp NumDn MinLoCord MaxHiCord MaxSubmerge Is_Ogee
23,21.5,3,0, 89, 89, , , .95, 0, 0,0,,
   -3096    5359    5559    5859    6159    6360    6559    6759    6959    7159
    7359    7959    8259    8559    8759    8959    9212    9459    9659    9859
   10059   10259   10459   10659   10859   11059   11259   11459   11759   11959
   12178   12459   12759   12959   12988   12999   13021   13259   13559   13859
   14159   14359   14554   14554   14859   14959   15059   15159   15545   15545
   15659   16082   16082   16159   16259   16359   16459   16559   16659   16759
   16859   16959   17059   17159   17259   17359   17459   17559   17659   17759
   17859   17959   18059   18137   18459   18659   18959   19159   19359   19559
   19759   19959   20259   20359   20559   20759   20859   23254   30000
   43.77   43.77   43.57   43.17   42.97   42.87   42.17   41.37   40.57   39.97
   39.37   37.47   36.77   35.97   35.07   34.17   32.97   32.17   31.77   31.27
   30.87   30.67   30.77   30.77   30.67   30.57   30.57   30.57   30.67   30.47
   29.97   30.37   30.27   30.47   30.47   29.87   30.47   30.47   30.87   31.37
   32.27   32.67   32.97   32.37   32.57   32.57   32.57   32.57   32.07   32.87
   32.87   33.17   32.77   32.87   32.77   32.67   32.87   32.97   32.97   32.97
   32.97   32.97   32.87   32.87   32.77   32.67   32.67   32.67   32.67   32.67
   32.67   32.67   32.77   32.87   34.17   35.27   36.77   37.77   38.97   40.27
   41.77   43.17   45.37   45.97   46.87   47.47   47.77   48.17   48.17
                                                                                
                                                                                
                                                                                
                                                                                
                                                                                
                   29.07   29.07   29.07   29.07   29.07   29.07   29.07   29.07
   29.07   29.07   29.07   29.07   29.07   29.07   29.07   29.07   29.07   29.07
   29.07   29.07   29.07
                                                                        
-3145.77 5309.23 5509.23 5809.23 6109.23 6310.23 6509.23 6709.23 6909.23 7109.23
 7309.23 7909.23 8209.23 8509.23 8709.23 8909.23 9162.23 9409.23 9609.23 9809.23
10009.2310209.2310409.2310609.2310809.2311009.2311209.2311409.2311709.2311909.23
12128.2312409.2312709.2312909.2312938.2312949.2312971.2313209.2313509.2313809.23
14109.2314309.2314504.2314504.2314809.2314909.2315009.2315109.2315495.2315495.23
15609.2316032.2316032.2316109.2316209.2316309.2316409.2316509.2316609.2316709.23
16809.2316909.2317009.2317109.2317209.2317309.2317409.2317509.2317609.2317709.23
17809.2317909.2318009.2318087.2318409.2318609.2318909.2319109.2319309.2319509.23
19709.2319909.2320209.2320309.2320509.2320709.2320809.2323204.2330457.23
   43.77   43.77   43.57   43.17   42.97   42.87   42.17   41.37   40.57   39.97
   39.37   37.47   36.77   35.97   35.07   34.17   32.97   32.17   31.77   31.27
   30.87   30.67   30.77   30.77   30.67   30.57   30.57   30.57   30.67   30.47
   29.97   30.37   30.27   30.47   30.47   29.87   30.47   30.47   30.87   31.37
   32.27   32.67   32.97   32.37   32.57   32.57   32.57   32.57   32.07   32.87
   32.87   33.17   32.77   32.87   32.77   32.67   32.87   32.97   32.97   32.97
   32.97   32.97   32.87   32.87   32.77   32.67   32.67   32.67   32.67   32.67
   32.67   32.67   32.77   32.87   34.17   35.27   36.77   37.77   38.97   40.27
   41.77   43.17   45.37   45.97   46.87   47.47   47.77   48.17   48.17
                                                                                
                                                                                
                                                                                
                                                                                
                                                                                
                   29.07   29.07   29.07   29.07   29.07   29.07   29.07   29.07
   29.07   29.07   29.07   29.07   29.07   29.07   29.07   29.07   29.07   29.07
   29.07   29.07   29.07
                                                                        
Pier Skew, UpSta & Num, DnSta & Num=  ,16678, 2 ,16630, 2 , 0 , 0 , 0 ,,
      25      25
     -15      30
      25      25
     -15      30
Pier Skew, UpSta & Num, DnSta & Num=  ,16851, 2 ,16803, 2 , 0 , 0 , 0 ,,
      25      25
     -15      30
      25      25
     -15      30
Pier Skew, UpSta & Num, DnSta & Num=  ,17024, 2 ,16976, 2 , 0 , 0 , 0 ,,
      25      25
     -15      30
      25      25
     -15      30
BR Coef=-1 , 0 , 0 ,, 0 ,,,.8,-1,,0,
WSPro=,,,, 1 ,,,, 0 ,,,, 0 ,,,,-1 ,-1 ,-1 , 0 , 0 , 0 , 0 , 0
BC Design=,, 0 ,, 0 ,,,,,,

Type RM Length L Ch R = 1 ,130210.8,2565.44,1409.05,1409.05
BEGIN DESCRIPTION:
sj24p513, Xsec 2/4 of South Pacific Railroad
xsec4/4 of Beaumonth HWY (old HWY 90)
Bank Station offset =     15403
---- FLOW CHANGE LOCATION
END DESCRIPTION:
XS GIS Cut Line= 6
     3216808.658     13897008.29     3210026.769    13895366.416
     3209114.894    13894384.842     3207516.504    13888933.189
     3203395.705    13887467.787     3196418.684    13882778.131
#Sta/Elev= 30
  457.23   47.34 2529.89   45.82 2785.77   37.61 3131.79   45.53 7120.67   38.67
 8033.73   30.05 8585.76   12.16 8971.44   25.5311260.15   15.3414249.12   21.99
14637.58   13.6715393.48   18.06 15524.4   27.53 15632.9   24.8215705.98   10.55
16131.42    9.1716407.42    3.7716544.42  -10.3316681.42   -2.2317031.42   -5.93
17329.42    9.8717932.42    7.3718404.97    39.618864.47   47.5521610.88   43.46
21695.88   46.3721743.73   65.32 21834.1    45.721969.03   44.29   27311   41.03
#Mann= 3 , 0 , 0
  457.23     .13       016131.42     .03       017329.42     .13       0
#XS Ineff= 2 , 0
  457.2315950.23   29.8718050.23  457.23   29.87
Permanent Ineff=
       F       F
Bank Sta=16131.42,17329.42
XS Rating Curve= 0
Exp/Cntr=.5,.3

Type RM Length L Ch R = 1 ,128801.7,146.16,150.22,123.25
BEGIN DESCRIPTION:
sj24p20, Xsec 1/4 of South Pacific Railroad
xsec 3/4  of Beaumonth HWY (old HWY 90)
Bank Station offset =     16364
END DESCRIPTION:
XS GIS Cut Line= 6
     3216804.084    13892031.597     3213726.779    13889491.476
     3205596.398     13886730.99     3203639.884    13886156.325
     3202112.762    13886036.484     3199806.949    13884817.697
#Sta/Elev= 30
       0   49.02 3802.05    40.8 3921.66   24.38 4457.48   18.78 5313.15   25.17
 5369.24    9.14 5609.64    8.41  5690.1   24.59 6714.74   26.07 8204.32   25.93
  8754.6   12.95 9150.86   20.67 9566.67     7.110644.94   12.2511332.01    1.94
11660.71   12.4711834.71    6.0711885.71  -17.4311935.71  -20.5312218.71    7.57
12570.71   10.5712878.34   24.0313664.28   19.3614299.57   41.1315203.17   34.95
16035.49   44.91 17344.1    43.517451.39    61.217519.26   44.3918777.31   44.61
#Mann= 3 , 0 , 0
       0     .13       011660.71     .03       012570.71     .13       0
#XS Ineff= 2 , 0
       0   11659   23.87   12571       0   23.87
Permanent Ineff=
       F       F
Bank Sta=11660.71,12570.71
XS Rating Curve= 0
Exp/Cntr=.5,.3

Type RM Length L Ch R = 3 ,128727  ,,,
BEGIN DESCRIPTION:
Beaumont Highway
END DESCRIPTION:
Bridge Culvert--1,0,-1,-1, 0
Deck Dist Width WeirC Skew NumUp NumDn MinLoCord MaxHiCord MaxSubmerge Is_Ogee
47,56,3,0, 60, 60, , , .95, 0, 0,0,,
       0    3590    3890    3990    4090    4490    4690    4890    5090    5324
    5324    5590    5639    5639    5990    6190    6690    6890    7390    7690
    8190    8490    8690    8990    9290    9890   10090   10290   10464   10464
   10690   10777   10777   10790   10990   11090   11390   11661   11661   11790
   11890   11990   12116   12190   12290   12390   12571   12571   13190   13231
   13357   13590   13690   13990   14290   14490   14690   15190   15216   18800
   32.17   31.87   25.57   24.27   23.97   23.87   25.17   25.27   24.87   24.77
   25.17   25.27   25.17   24.67   25.07   24.67   25.27   24.77   24.97   24.47
   25.07   24.47   24.47   25.17   24.47   24.77   24.07   24.07   24.47   24.77
   24.97   24.87   24.37   24.07   24.17   23.97   26.07   30.07   29.77   31.37
   32.17   32.47   32.37   32.77   30.87   29.87    29.6   28.37   26.37   27.17
   27.37   30.27   32.17   38.87   42.37   43.27   43.57   42.27   41.77   41.77
     -30     -30     -30     -30     -30     -30     -30     -30     -30     -30
     -30     -30     -30     -30     -30     -30     -30     -30     -30     -30
     -30     -30     -30     -30     -30     -30     -30     -30     -30     -30
     -30     -30     -30     -30     -30     -30     -30     -30   29.47   29.47
   29.47   29.47   29.47   29.47   29.47   29.47   29.47     -30     -30     -30
     -30     -30     -30     -30     -30     -30     -30     -30     -30     -30
  160.77 3589.77 3889.77 3989.77 4089.77 4489.77 4689.77 4889.77 5089.77 5323.77
 5323.77 5589.77 5638.77 5638.77 5989.77 6189.77 6689.77 6889.77 7389.77 7689.77
 8189.77 8489.77 8689.77 8989.77 9289.77 9889.7710089.7710289.7710463.7710463.77
10689.7710776.7710776.7710789.7710989.7711089.7711389.7711660.7711660.7711789.77
11889.7711989.7712115.7712189.7712289.7712389.7712570.7712570.7713189.7713230.77
13356.7713589.7713689.7713989.7714289.7714489.7714689.7715189.7715215.7719314.77
   32.17   31.87   25.57   24.27   23.97   23.87   25.17   25.27   24.87   24.77
   25.17   25.27   25.17   24.67   25.07   24.67   25.27   24.77   24.97   24.47
   25.07   24.47   24.47   25.17   24.47   24.77   24.07   24.07   24.47   24.77
   24.97   24.87   24.37   24.07   24.17   23.97   26.07   30.07   29.77   31.37
   32.17   32.47   32.37   32.77   30.87   29.87    29.6   28.37   26.37   27.17
   27.37   30.27   32.17   38.87   42.37   43.27   43.57   42.27   41.77   41.77
     -30     -30     -30     -30     -30     -30     -30     -30     -30     -30
     -30     -30     -30     -30     -30     -30     -30     -30     -30     -30
     -30     -30     -30     -30     -30     -30     -30     -30     -30     -30
     -30     -30     -30     -30     -30     -30     -30     -30   29.47   29.47
   29.47   29.47   29.47   29.47   29.47   29.47   29.47     -30     -30     -30
     -30     -30     -30     -30     -30     -30     -30     -30     -30     -30
Pier Skew, UpSta & Num, DnSta & Num=  ,11935, 2 ,11931, 2 , 0 , 0 , 0 ,,
       7       7
     -25      30
       7       7
     -25      30
Pier Skew, UpSta & Num, DnSta & Num=  ,12020, 2 ,12018, 2 , 0 , 0 , 0 ,,
       7       7
     -25      30
       7       7
     -25      30
Pier Skew, UpSta & Num, DnSta & Num=  ,12105, 2 ,12105, 2 , 0 , 0 , 0 ,,
       7       7
     -25      30
       7       7
     -25      30
BR Coef=-1 , 0 , 0 ,, 0 ,,,.8,-1,,0,
WSPro=,,,, 1 ,,,, 0 ,,,, 0 ,,,,-1 ,-1 ,-1 , 0 , 0 , 0 , 0 , 0
BC Design=,, 0 ,, 0 ,,,,,,

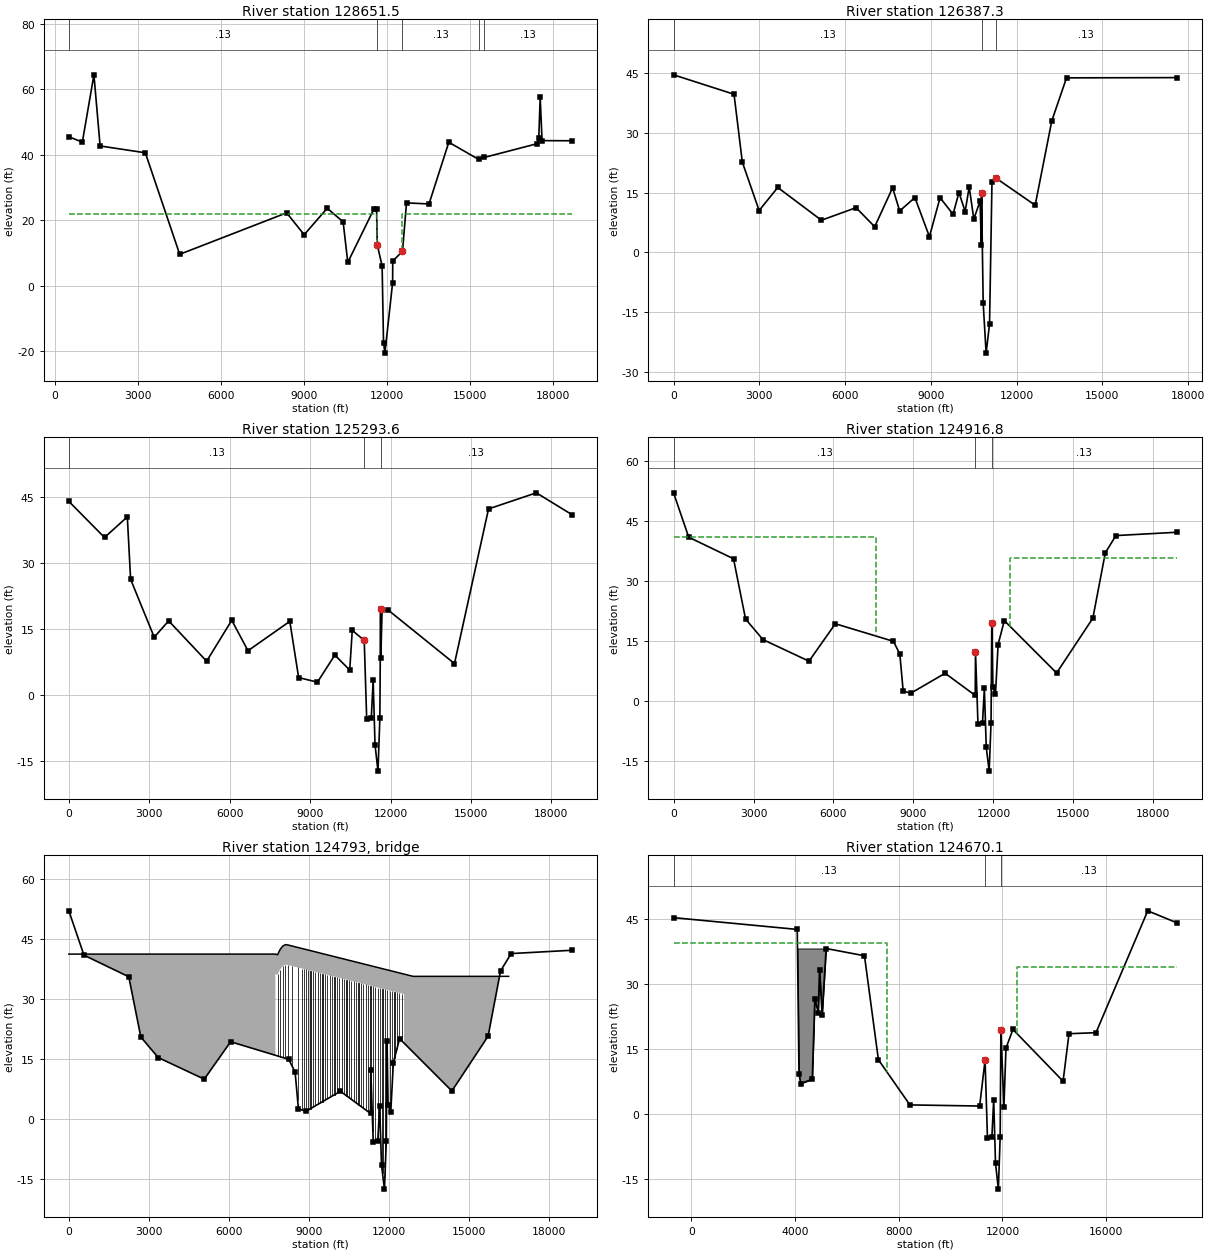
Type RM Length L Ch R = 1 ,128651.5,2797.88,2264.25,2117.27
BEGIN DESCRIPTION:
sj24p17, Xsec 2/4  of Beaumont HWY (old HWY 90)
Bank Station offset =     16879
---- FLOW CHANGE LOCATION
END DESCRIPTION:
XS GIS Cut Line= 6
     3216817.805    13891040.619     3215100.758    13889917.915
     3207236.356    13887115.628     3204103.383    13886151.636
     3202488.825    13885967.831     3199919.491    13884683.164
#Sta/Elev= 30
  514.77   45.54 1003.45   43.89 1421.63   64.44 1645.21   42.72 3279.11   40.64
 4520.71    9.64 8385.42   22.31 9018.18   15.62 9848.33   23.6910425.32   19.57
10594.13    7.1911538.41   23.4511634.08   23.3911660.71   12.4711834.71    6.07
11885.71  -17.4311935.71  -20.5312213.71     .9712218.71    7.5712570.71   10.57
12715.76   25.3513528.34   25.0114244.29   43.8615323.45   38.6115531.33   39.23
 17434.7   43.4117495.83   45.1717546.15   57.5717613.23   44.3518697.39   44.31
#Mann= 5 ,-1 , 0
  514.77     .13       011660.71     .03       012570.71     .13       0
15323.45     .99       015531.33     .13       0
#XS Ineff= 2 , 0
  514.7711658.77      2212570.77  514.77      22
Permanent Ineff=
       F       F
Bank Sta=11660.71,12570.71
XS Rating Curve= 0
Exp/Cntr=.5,.3

Type RM Length L Ch R = 1 ,126387.3,532.75,1093.7,1616.56
BEGIN DESCRIPTION:
sj23p75, Xsec 1/4  of Beaumont HWY (old HWY 90)
Bank Station offset =     14728
END DESCRIPTION:
XS GIS Cut Line= 6
     3215405.155    13890063.497     3211625.454     13886466.08
     3209222.267    13885024.167     3206498.512    13884562.722
     3203999.339    13884383.317     3199800.588    13883481.371
#Sta/Elev= 30
       0   44.53 2114.73   39.66 2405.07   22.65 2992.51   10.52 3644.64   16.29
 5172.14    8.08 6383.58   11.23 7034.62    6.45 7661.93   16.22 7908.74    10.4
 8440.38   13.77 8949.55    3.96 9320.86   13.73 9775.19    9.58 9982.33   15.03
10198.63   10.2610340.57   16.4310502.38    8.3710721.52   12.9110762.71    1.95
10771.92   14.8710829.92  -12.7310931.92  -25.2311051.92  -17.9311136.92   17.57
11271.92   18.6712648.04   11.8413229.25   32.9913744.37   43.7717601.18   43.83
#Mann= 3 , 0 , 0
       0     .13       010771.92     .03       011271.92     .13       0
Bank Sta=10771.92,11271.92
XS Rating Curve= 0
Exp/Cntr=.3,.1

Type RM Length L Ch R = 1 ,125293.6,138.51,376.8,487.54
BEGIN DESCRIPTION:
Copy of sj23p38, Xsec 4/4 of US HWY 90
Bank Station offset =     16988
END DESCRIPTION:
XS GIS Cut Line= 6
     3215458.094    13890010.558     3211392.537    13886147.765
     3209479.049     13884713.56     3206862.274    13883629.845
     3200307.122    13881409.552     3199408.431    13880933.775
#Sta/Elev= 30
       0   44.08 1331.04   35.85 2181.92   40.55 2304.61   26.31 3185.41   13.11
 3723.96   16.84 5140.43    7.64  6077.9   16.97  6682.6   10.03 8243.21   16.73
 8571.78    3.91 9274.11    2.86 9920.99    9.0410478.31    5.6310572.21   14.67
11018.58   12.3811111.58   -5.6211281.58   -5.4211351.58    3.2811421.58  -11.42
11531.58  -17.4211601.58   -5.4211629.58   19.4811638.03    8.4511684.44   19.32
11906.22   19.3314385.37     7.115655.49   42.3617437.92   46.0318771.01   41.04
#Mann= 3 , 0 , 0
       0     .13       011018.58     .03       011629.58     .13       0
Bank Sta=11018.58,11629.58
XS Rating Curve= 0
Exp/Cntr=.7,.5

Type RM Length L Ch R = 1 ,124916.8,286.73,246.71,563.78
BEGIN DESCRIPTION:
Copy of sj23p38, Xsec 3/4 of US HWY 90
ROB and LOB reach lengths > channel reach length due to flow contraction at the structure.
Bank Station offset =     16680
END DESCRIPTION:
XS GIS Cut Line= 6
     3215669.849    13890076.731     3211560.353    13886197.522
     3209346.497     13884528.59     3206064.504    13882968.159
     3205461.948     13882917.07     3199940.275    13880163.556
#Sta/Elev= 30
       0   52.11  567.89   41.03 2249.29   35.63 2701.71   20.57 3354.96   15.44
  5080.2   10.05 6069.77    19.4 8248.77   15.01 8488.45   11.84 8613.17    2.65
 8890.04    2.0110188.34    7.0311317.71    1.4911327.42   12.3811420.42   -5.62
11590.42   -5.4211660.42    3.2811730.42  -11.4211840.42  -17.4211910.42   -5.42
11938.42   19.4811977.47    3.5712077.39    1.7612174.87   14.2112408.92   20.18
14370.03     7.115729.96   20.7916196.54    37.1 16594.4   41.4318879.03   42.26
#Mann= 3 , 0 , 0
       0     .13       011327.42     .03       011938.42     .13       0
#XS Ineff= 2 , 0
       0 7611.95   41.13 12634.5       0   35.74
Permanent Ineff=
       F       F
Bank Sta=11327.42,11938.42
XS Rating Curve= 0
Exp/Cntr=.7,.5

Type RM Length L Ch R = 3 ,124793  ,,,
BEGIN DESCRIPTION:
US Hwy 90
END DESCRIPTION:
Bridge Culvert--1,0,-1,-1, 0
Deck Dist Width WeirC Skew NumUp NumDn MinLoCord MaxHiCord MaxSubmerge Is_Ogee
26,195.5,2.6,0, 58, 58, , , .95, 0, 0,0,,
       0    7747    7748    7828    7928    8028    8128    8228    8328    8428
    8528    8628    8728    8828    8928    9028    9128    9228    9328    9428
    9528    9628    9728    9828    9928   10028   10128   10228   10328   10428
   10528   10628   10728   10828   10928   11028   11128   11228   11328   11428
   11528   11628   11728   11828   11928   12028   12128   12228   12328   12428
   12528   12578   12579   12628   12728   12828   12928   16500
    41.3    41.3    41.3   41.13   42.45   43.32   43.67   43.57    43.4   43.23
   43.06    42.9   42.73   42.56    42.4   42.23   42.06    41.9   41.73   41.56
   41.39   41.23   41.06    40.9   40.73   40.56   40.39   40.23   40.06   39.89
   39.72   39.56   39.39   39.22   39.06   38.89   38.72   38.56   38.39   38.22
   38.05   37.89   37.72   37.55   37.39   37.22   37.05   36.89   36.72   36.55
   36.38    36.3    36.3   36.22   36.05   35.88   35.74   35.74
                    36.3   36.13   37.45   38.32   38.67   38.57    38.4   38.23
   38.06    37.9   37.73   37.56    37.4   37.23   37.06    36.9   36.73   36.56
   36.39   36.23   36.06    35.9   35.73   35.56   35.39   35.23   35.06   34.89
   34.72   34.56   34.39   34.22   34.06   33.89   33.72   33.56   33.39   33.22
   33.05   32.89   32.72   32.55   32.39   32.22   32.05   31.89   31.72   31.55
   31.38    31.3
  -690.8  7667.2  7668.2  7748.2  7848.2  7948.2  8048.2  8148.2  8248.2  8348.2
  8448.2  8548.2  8648.2  8748.2  8848.2  8948.2  9048.2  9148.2  9248.2  9348.2
  9448.2  9548.2  9648.2  9748.2  9848.2  9948.2 10048.2 10148.2 10248.2 10348.2
 10448.2 10548.2 10648.2 10748.2 10848.2 10948.2 11048.2 11148.2 11248.2 11348.2
 11448.2 11548.2 11648.2 11748.2 11848.2 11948.2 12048.2 12148.2 12248.2 12348.2
 12448.2 12498.2 12499.2 12548.2 12648.2 12748.2 12848.2 16809.2
    41.3    41.3    41.3   41.13   42.45   43.32   43.67   43.57    43.4   43.23
   43.06    42.9   42.73   42.56    42.4   42.23   42.06    41.9   41.73   41.56
   41.39   41.23   41.06    40.9   40.73   40.56   40.39   40.23   40.06   39.89
   39.72   39.56   39.39   39.22   39.06   38.89   38.72   38.56   38.39   38.22
   38.05   37.89   37.72   37.55   37.39   37.22   37.05   36.89   36.72   36.55
   36.38    36.3    36.3   36.22   36.05   35.88   35.74   35.74
                    36.3   36.13   37.45   38.32   38.67   38.57    38.4   38.23
   38.06    37.9   37.73   37.56    37.4   37.23   37.06    36.9   36.73   36.56
   36.39   36.23   36.06    35.9   35.73   35.56   35.39   35.23   35.06   34.89
   34.72   34.56   34.39   34.22   34.06   33.89   33.72   33.56   33.39   33.22
   33.05   32.89   32.72   32.55   32.39   32.22   32.05   31.89   31.72   31.55
   31.38    31.3
Pier Skew, UpSta & Num, DnSta & Num=  ,7838, 2 ,7758, 2 , 0 , 0 , 0 ,,
     3.5     3.5
     -20      50
     3.5     3.5
     -20      50
Pier Skew, UpSta & Num, DnSta & Num=  ,7928, 2 ,7848, 2 , 0 , 0 , 0 ,,
     3.5     3.5
     -20      50
     3.5     3.5
     -20      50
Pier Skew, UpSta & Num, DnSta & Num=  ,8018, 2 ,7938, 2 , 0 , 0 , 0 ,,
     3.5     3.5
     -20      50
     3.5     3.5
     -20      50
Pier Skew, UpSta & Num, DnSta & Num=  ,8115, 2 ,8035, 2 , 0 , 0 , 0 ,,
     3.5     3.5
     -20      50
     3.5     3.5
     -20      50
Pier Skew, UpSta & Num, DnSta & Num=  ,8207, 2 ,8127, 2 , 0 , 0 , 0 ,,
     3.5     3.5
     -20      50
     3.5     3.5
     -20      50
Pier Skew, UpSta & Num, DnSta & Num=  ,8382, 2 ,8302, 2 , 0 , 0 , 0 ,,
     3.5     3.5
     -20      50
     3.5     3.5
     -20      50
Pier Skew, UpSta & Num, DnSta & Num=  ,8582, 2 ,8502, 2 , 0 , 0 , 0 ,,
     3.5     3.5
     -20      50
     3.5     3.5
     -20      50
Pier Skew, UpSta & Num, DnSta & Num=  ,8757, 2 ,8677, 2 , 0 , 0 , 0 ,,
     3.5     3.5
     -20      50
     3.5     3.5
     -20      50
Pier Skew, UpSta & Num, DnSta & Num=  ,8818, 2 ,8738, 2 , 0 , 0 , 0 ,,
     3.5     3.5
     -20      50
     3.5     3.5
     -20      50
Pier Skew, UpSta & Num, DnSta & Num=  ,8888, 2 ,8808, 2 , 0 , 0 , 0 ,,
     3.5     3.5
     -20      50
     3.5     3.5
     -20      50
Pier Skew, UpSta & Num, DnSta & Num=  ,8978, 2 ,8898, 2 , 0 , 0 , 0 ,,
     3.5     3.5
     -20      50
     3.5     3.5
     -20      50
Pier Skew, UpSta & Num, DnSta & Num=  ,9068, 2 ,8988, 2 , 0 , 0 , 0 ,,
     3.5     3.5
     -20      50
     3.5     3.5
     -20      50
Pier Skew, UpSta & Num, DnSta & Num=  ,9158, 2 ,9078, 2 , 0 , 0 , 0 ,,
     3.5     3.5
     -20      50
     3.5     3.5
     -20      50
Pier Skew, UpSta & Num, DnSta & Num=  ,9248, 2 ,9168, 2 , 0 , 0 , 0 ,,
     3.5     3.5
     -20      50
     3.5     3.5
     -20      50
Pier Skew, UpSta & Num, DnSta & Num=  ,9338, 2 ,9258, 2 , 0 , 0 , 0 ,,
     3.5     3.5
     -20      50
     3.5     3.5
     -20      50
Pier Skew, UpSta & Num, DnSta & Num=  ,9428, 2 ,9348, 2 , 0 , 0 , 0 ,,
     3.5     3.5
     -20      50
     3.5     3.5
     -20      50
Pier Skew, UpSta & Num, DnSta & Num=  ,9518, 2 ,9438, 2 , 0 , 0 , 0 ,,
     3.5     3.5
     -20      50
     3.5     3.5
     -20      50
Pier Skew, UpSta & Num, DnSta & Num=  ,9608, 2 ,9528, 2 , 0 , 0 , 0 ,,
     3.5     3.5
     -20      50
     3.5     3.5
     -20      50
Pier Skew, UpSta & Num, DnSta & Num=  ,9698, 2 ,9618, 2 , 0 , 0 , 0 ,,
     3.5     3.5
     -20      50
     3.5     3.5
     -20      50
Pier Skew, UpSta & Num, DnSta & Num=  ,9788, 2 ,9708, 2 , 0 , 0 , 0 ,,
     3.5     3.5
     -20      50
     3.5     3.5
     -20      50
Pier Skew, UpSta & Num, DnSta & Num=  ,9878, 2 ,9798, 2 , 0 , 0 , 0 ,,
     3.5     3.5
     -20      50
     3.5     3.5
     -20      50
Pier Skew, UpSta & Num, DnSta & Num=  ,9968, 2 ,9888, 2 , 0 , 0 , 0 ,,
     3.5     3.5
     -20      50
     3.5     3.5
     -20      50
Pier Skew, UpSta & Num, DnSta & Num=  ,10058, 2 ,9978, 2 , 0 , 0 , 0 ,,
     3.5     3.5
     -20      50
     3.5     3.5
     -20      50
Pier Skew, UpSta & Num, DnSta & Num=  ,10148, 2 ,10068, 2 , 0 , 0 , 0 ,,
     3.5     3.5
     -20      50
     3.5     3.5
     -20      50
Pier Skew, UpSta & Num, DnSta & Num=  ,10238, 2 ,10158, 2 , 0 , 0 , 0 ,,
     3.5     3.5
     -20      50
     3.5     3.5
     -20      50
Pier Skew, UpSta & Num, DnSta & Num=  ,10328, 2 ,10248, 2 , 0 , 0 , 0 ,,
     3.5     3.5
     -20      50
     3.5     3.5
     -20      50
Pier Skew, UpSta & Num, DnSta & Num=  ,10418, 2 ,10338, 2 , 0 , 0 , 0 ,,
     3.5     3.5
     -20      50
     3.5     3.5
     -20      50
Pier Skew, UpSta & Num, DnSta & Num=  ,10508, 2 ,10428, 2 , 0 , 0 , 0 ,,
     3.5     3.5
     -20      50
     3.5     3.5
     -20      50
Pier Skew, UpSta & Num, DnSta & Num=  ,10598, 2 ,10518, 2 , 0 , 0 , 0 ,,
     3.5     3.5
     -20      50
     3.5     3.5
     -20      50
Pier Skew, UpSta & Num, DnSta & Num=  ,10688, 2 ,10608, 2 , 0 , 0 , 0 ,,
     3.5     3.5
     -20      50
     3.5     3.5
     -20      50
Pier Skew, UpSta & Num, DnSta & Num=  ,10778, 2 ,10698, 2 , 0 , 0 , 0 ,,
     3.5     3.5
     -20      50
     3.5     3.5
     -20      50
Pier Skew, UpSta & Num, DnSta & Num=  ,10868, 2 ,10788, 2 , 0 , 0 , 0 ,,
     3.5     3.5
     -20      50
     3.5     3.5
     -20      50
Pier Skew, UpSta & Num, DnSta & Num=  ,10958, 2 ,10878, 2 , 0 , 0 , 0 ,,
     3.5     3.5
     -20      50
     3.5     3.5
     -20      50
Pier Skew, UpSta & Num, DnSta & Num=  ,11048, 2 ,10968, 2 , 0 , 0 , 0 ,,
     3.5     3.5
     -20      50
     3.5     3.5
     -20      50
Pier Skew, UpSta & Num, DnSta & Num=  ,11138, 2 ,11058, 2 , 0 , 0 , 0 ,,
     3.5     3.5
     -20      50
     3.5     3.5
     -20      50
Pier Skew, UpSta & Num, DnSta & Num=  ,11228, 2 ,11148, 2 , 0 , 0 , 0 ,,
     3.5     3.5
     -20      50
     3.5     3.5
     -20      50
Pier Skew, UpSta & Num, DnSta & Num=  ,11318, 2 ,11238, 2 , 0 , 0 , 0 ,,
     3.5     3.5
     -20      50
     3.5     3.5
     -20      50
Pier Skew, UpSta & Num, DnSta & Num=  ,11408, 2 ,11328, 2 , 0 , 0 , 0 ,,
     3.5     3.5
     -20      50
     3.5     3.5
     -20      50
Pier Skew, UpSta & Num, DnSta & Num=  ,11498, 2 ,11418, 2 , 0 , 0 , 0 ,,
     3.5     3.5
     -20      50
     3.5     3.5
     -20      50
Pier Skew, UpSta & Num, DnSta & Num=  ,11588, 2 ,11508, 2 , 0 , 0 , 0 ,,
     3.5     3.5
     -20      50
     3.5     3.5
     -20      50
Pier Skew, UpSta & Num, DnSta & Num=  ,11678, 2 ,11598, 2 , 0 , 0 , 0 ,,
     3.5     3.5
     -20      50
     3.5     3.5
     -20      50
Pier Skew, UpSta & Num, DnSta & Num=  ,11768, 2 ,11688, 2 , 0 , 0 , 0 ,,
     3.5     3.5
     -20      50
     3.5     3.5
     -20      50
Pier Skew, UpSta & Num, DnSta & Num=  ,11858, 2 ,11778, 2 , 0 , 0 , 0 ,,
     3.5     3.5
     -20      50
     3.5     3.5
     -20      50
Pier Skew, UpSta & Num, DnSta & Num=  ,11948, 2 ,11868, 2 , 0 , 0 , 0 ,,
     3.5     3.5
     -20      50
     3.5     3.5
     -20      50
Pier Skew, UpSta & Num, DnSta & Num=  ,12038, 2 ,11958, 2 , 0 , 0 , 0 ,,
     3.5     3.5
     -20      50
     3.5     3.5
     -20      50
Pier Skew, UpSta & Num, DnSta & Num=  ,12128, 2 ,12048, 2 , 0 , 0 , 0 ,,
     3.5     3.5
     -20      50
     3.5     3.5
     -20      50
Pier Skew, UpSta & Num, DnSta & Num=  ,12218, 2 ,12138, 2 , 0 , 0 , 0 ,,
     3.5     3.5
     -20      50
     3.5     3.5
     -20      50
Pier Skew, UpSta & Num, DnSta & Num=  ,12308, 2 ,12228, 2 , 0 , 0 , 0 ,,
     3.5     3.5
     -20      50
     3.5     3.5
     -20      50
Pier Skew, UpSta & Num, DnSta & Num=  ,12398, 2 ,12318, 2 , 0 , 0 , 0 ,,
     3.5     3.5
     -20      50
     3.5     3.5
     -20      50
Pier Skew, UpSta & Num, DnSta & Num=  ,12488, 2 ,12408, 2 , 0 , 0 , 0 ,,
     3.5     3.5
     -20      50
     3.5     3.5
     -20      50
BR Coef=-1 , 1 , 1 ,.9, 0 ,,,.8,-1,1.2,0,
WSPro=,,,, 1 ,,,, 0 ,,,, 0 ,,,,-1 ,-1 ,-1 , 0 , 0 , 0 , 0 , 0
BC Design=,, 0 ,, 0 ,,,,,,

Type RM Length L Ch R = 1 ,124670.1,435.7,362.55,271.62
BEGIN DESCRIPTION:
sj23p38, Xsec 2/4 of US HWY 90
Bank Station offset =     15989
Ponded areas on LOB blocked
END DESCRIPTION:
XS GIS Cut Line= 6
      3217585.36    13888068.205     3214252.939     13886594.25
     3210258.162    13884515.869     3206026.157    13882729.082
     3205769.522    13882389.801     3200157.763    13879860.017
#Sta/Elev= 30
  -690.8   45.34 4081.49   42.62 4149.23     9.1 4214.63    6.99  4661.3    7.98
 4759.19   26.55  4890.2   23.41 4940.72   33.29 5040.82   22.81 5195.24   38.21
 6674.58   36.53 7212.49   12.49 8427.76    2.0511118.78    1.7911327.42   12.38
11420.42   -5.6211590.42   -5.4211660.42    3.2811730.42  -11.4211840.42  -17.42
11910.42   -5.4211938.42   19.4812054.72    1.5912134.35   15.1712402.75    19.5
14337.77    7.5314565.82   18.5115607.02   18.7517603.77   46.9218724.74   44.16
#Mann= 3 , 0 , 0
  -690.8     .13       011327.42     .03       011938.42     .13       0
#XS Ineff= 2 , 0
  -690.8  7536.7    39.5 12559.2  -690.8      34
Permanent Ineff=
       F       F
#Block Obstruct= 1 ,-1
 4081.49 5195.24   38.21
Bank Sta=11327.42,11938.42
XS Rating Curve= 0
Exp/Cntr=.7,.5