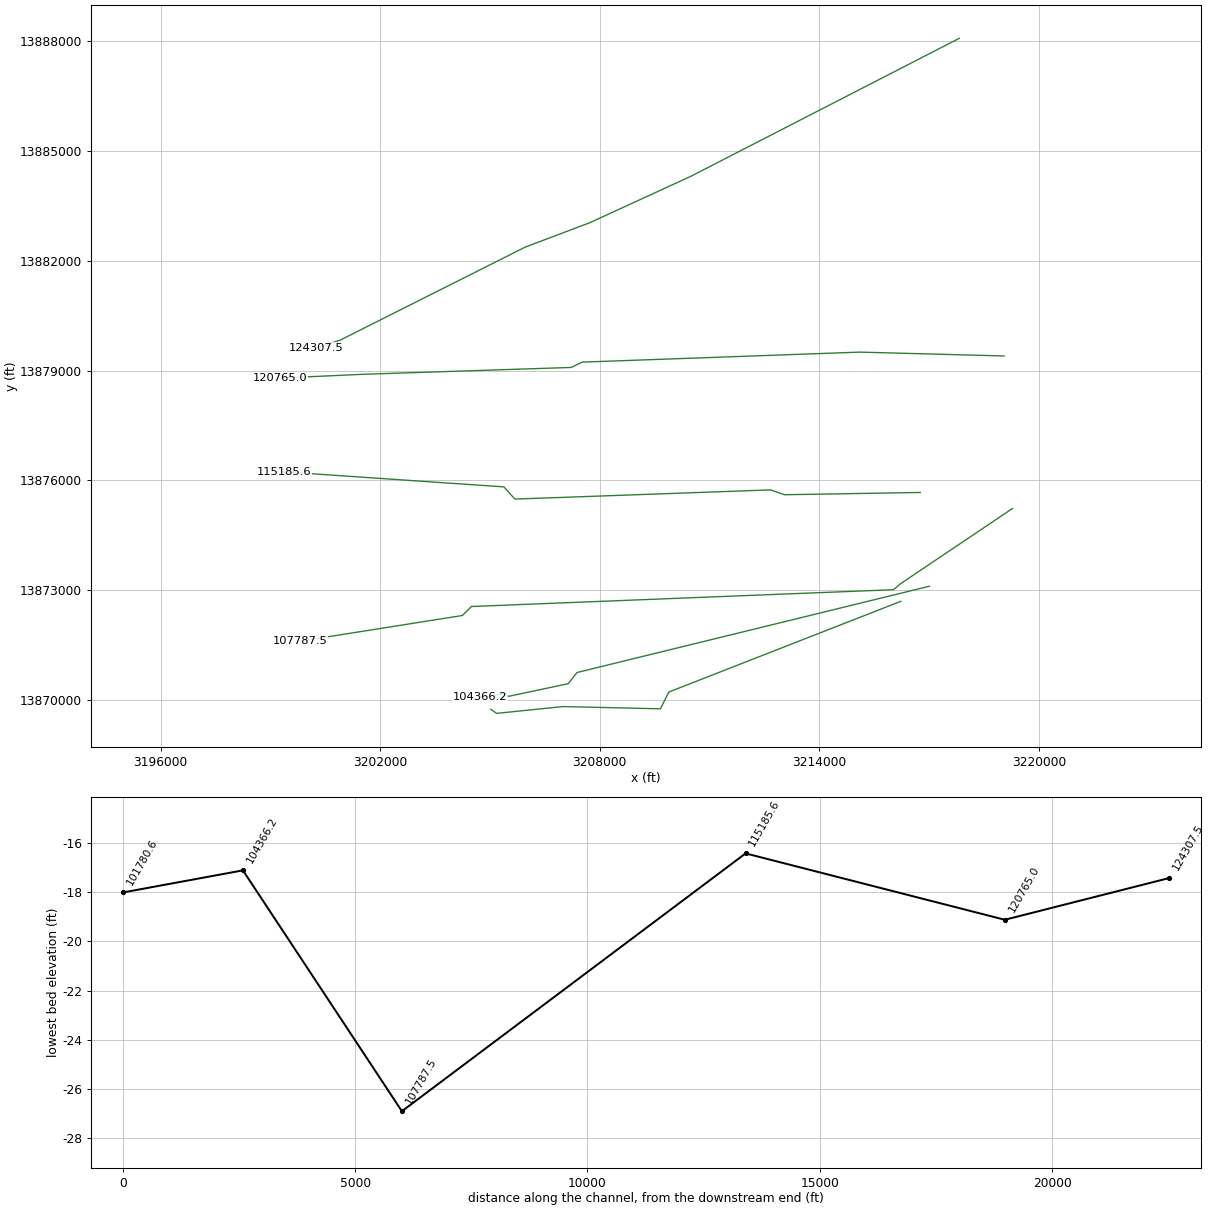
HEC-RAS study G103-00-00.prj: G103-00-00SJ

--- G103-00-00.g01 (geometry) --- (continued)

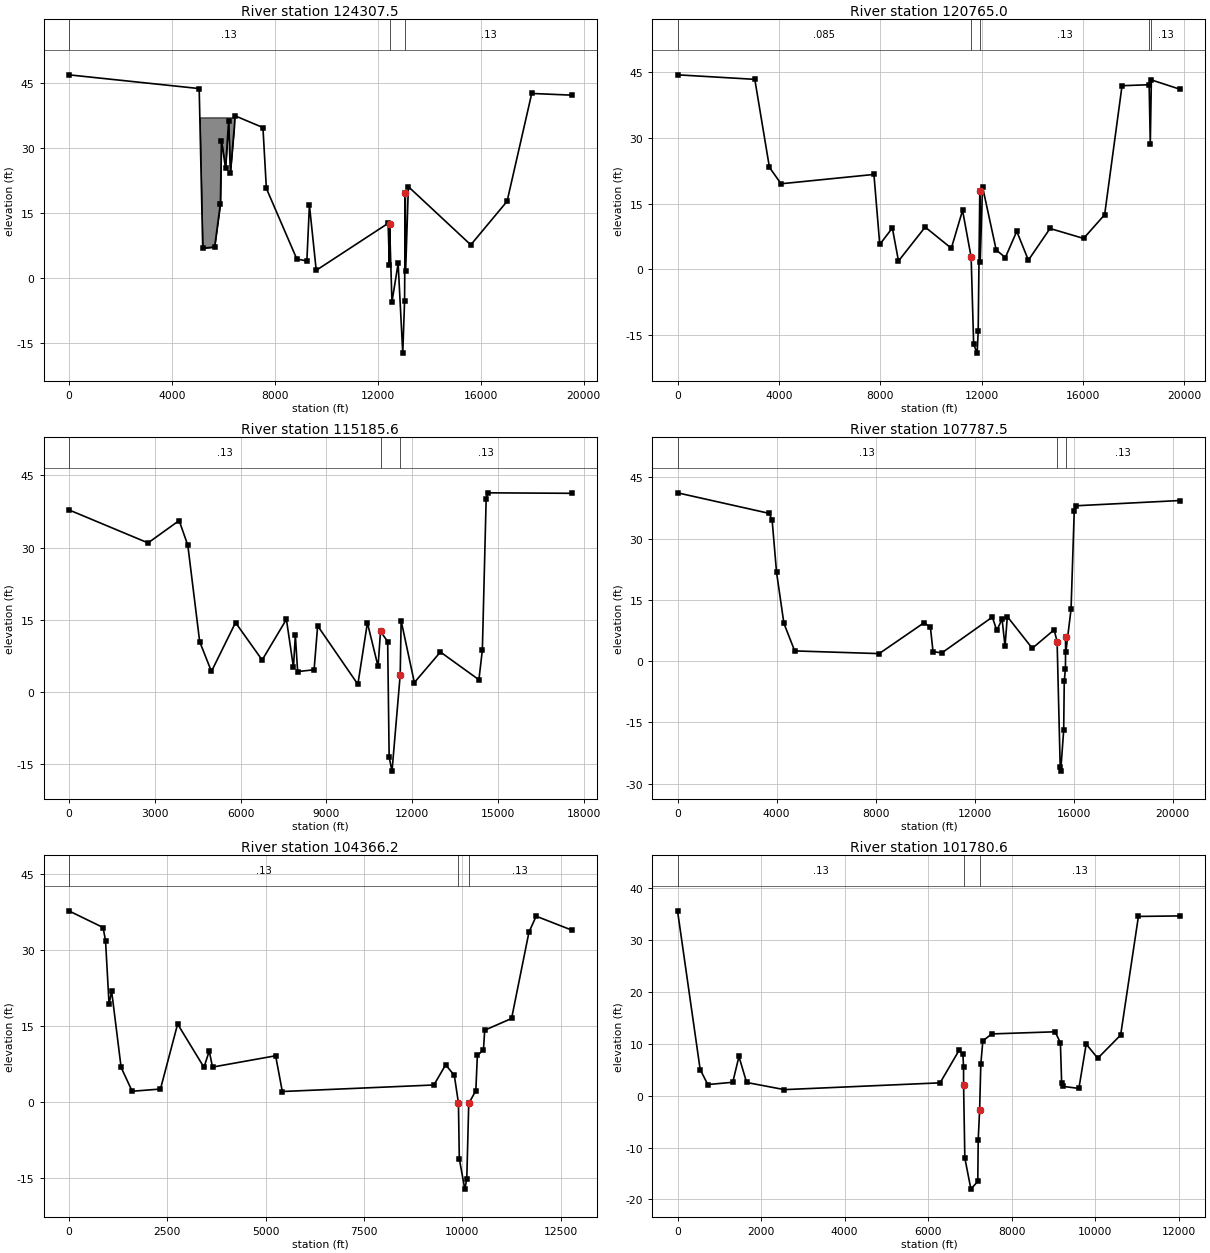
Type RM Length L Ch R = 1 ,124307.5,4906.93,3542.46,2799.46
BEGIN DESCRIPTION:
Copy of sj23p38, Xsec 1/4 of US HWY 90
Bank Station offset =     15549
Ponded areas on LOB blocked
END DESCRIPTION:
XS GIS Cut Line= 6
     3217823.449    13888078.565     3210486.387    13884307.154
     3207732.614    13883042.666      3205962.04    13882373.481
     3200906.926    13879831.761     3200246.125    13879620.304
#Sta/Elev= 30
       0   46.81  5063.8   43.64 5201.24    6.81 5662.35    7.06 5888.15   17.09
 5928.08   31.65 6087.65   25.24    6207   36.18 6273.18   24.08 6464.43   37.33
 7540.04   34.64 7673.02    20.6 8854.37    4.32 9245.72    3.84 9345.03   16.75
 9609.56    1.6912401.48   12.5412451.16    2.9912457.61   12.3812550.61   -5.62
12790.61    3.2812970.61  -17.4213040.61   -5.4213068.61   19.4813082.45    1.58
13187.96      2115612.65    7.5717022.05   17.6217979.04   42.5119526.04   42.12
#Mann= 3 , 0 , 0
       0     .13       012457.61     .03       013068.61     .13       0
#Block Obstruct= 1 ,-1
  5063.8 6424.97   36.98
Bank Sta=12457.61,13068.61
XS Rating Curve= 0
Exp/Cntr=.3,.1

Type RM Length L Ch R = 1 ,120765.0,3693.92,5579.41,3346.95
BEGIN DESCRIPTION:
sj22p64
Bank Station offset =     18234
END DESCRIPTION:
XS GIS Cut Line= 6
      3219048.82    13879400.124     3215111.418    13879505.313
     3207516.623    13879231.765     3207220.691    13879086.447
     3201548.819    13878900.124     3199257.153    13878795.957
#Sta/Elev= 30
       0   44.36 3048.89   43.33 3626.29   23.25 4084.97   19.51 7749.68   21.64
 7979.26    5.66 8476.25    9.43 8718.36    1.89 9771.32    9.6310803.69     4.8
11246.83   13.4411585.02    2.7811685.02  -17.1211823.02  -19.1211863.02  -14.12
11927.02   17.7811942.09    1.6412034.97   18.8212574.78     4.412935.22    2.68
13385.65    8.6713843.93    2.08 14697.7    9.3116022.21    7.0416852.53   12.45
17539.38   41.8818609.07    42.118654.11   28.5518696.53    43.219837.37   41.05
#Mann= 5 ,-1 , 0
       0    .085       011585.02     .03       011927.02     .13       0
18609.07     .99       018696.53     .13       0
Bank Sta=11585.02,11927.02
XS Rating Curve= 0
Exp/Cntr=.3,.1

Type RM Length L Ch R = 1 ,115185.6,4971.4,7398.15,4356.34
BEGIN DESCRIPTION:
sj21p565
Bank Station offset =     21009
---- FLOW CHANGE LOCATION
END DESCRIPTION:
XS GIS Cut Line= 6
     3216757.153    13875670.957      3213048.82    13875608.457
     3212668.095    13875740.862      3205682.25    13875489.649
     3205381.121    13875823.682     3199382.153    13876233.457
#Sta/Elev= 30
       0   37.83 2768.67   30.96 3855.42    35.6 4158.13   30.47 4572.43   10.47
 4983.85    4.27 5825.24   14.42 6755.45    6.65 7603.26   15.09 7850.05    5.12
  7914.7   11.82 7995.39    4.25 8570.13    4.62 8694.82   13.7410099.82     1.6
10432.78   14.3710805.29    5.3110890.99   12.5811140.99   10.4811192.99  -13.52
11292.99  -16.4211578.99    3.5811611.49    14.812073.95    1.9712984.29    8.31
14329.01    2.5514449.73    8.7414582.47   40.1214639.93   41.3617566.11   41.26
#Mann= 3 , 0 , 0
       0     .13       010890.99     .03       011578.99     .13       0
Bank Sta=10890.99,11578.99
XS Rating Curve= 0
Exp/Cntr=.3,.1

Type RM Length L Ch R = 1 ,107787.5,800.15,3421.31,3134.05
BEGIN DESCRIPTION:
sj20p13
Bank Station offset =     18226
END DESCRIPTION:
XS GIS Cut Line= 6
     3219277.986    13875233.457     3216219.055    13873176.992
     3216028.808    13873014.234     3204495.035     13872554.81
     3204248.002    13872309.221     3199819.653    13871608.457
#Sta/Elev= 30
       0    41.2 3696.83   36.18 3820.68   34.61 4000.97   21.71 4297.58    9.26
 4733.75    2.51 8146.93    1.85 9960.66    9.4110215.87    8.31 10322.1    2.35
10677.04    2.0212716.96   10.7812898.83    7.5413112.21   10.2913231.17    3.62
13323.34   10.9114332.42    3.1515214.82    7.6815334.85    4.7915459.85  -25.91
15479.85  -26.9115600.85  -16.9115623.85   -4.9115671.85   -1.8115680.85    5.99
 15689.8    2.3215898.62   12.7416027.11   36.7816088.83   38.0320311.06   39.32
#Mann= 3 , 0 , 0
       0     .13       015334.85     .03       015680.85     .13       0
Bank Sta=15334.85,15680.85
XS Rating Curve= 0
Exp/Cntr=.3,.1

Type RM Length L Ch R = 1 ,104366.2,367.32,2585.55,1239.94
BEGIN DESCRIPTION:
sj19p47
Bank Station offset =     10153
END DESCRIPTION:
XS GIS Cut Line= 6
     3217007.153    13873108.457     3207379.992    13870751.426
     3207139.079    13870445.837      3205502.94    13870099.267
     3205419.464    13870171.823     3204734.535    13870079.621
#Sta/Elev= 30
       0    37.8  870.74   34.51  933.37   31.92 1023.04   19.33 1087.96      22
 1329.25    6.91 1610.07     2.2 2329.48    2.64 2765.23   15.46  3435.1    6.92
 3568.85   10.15 3651.74    6.97 5255.74     9.2 5425.81    2.15 9278.56    3.44
 9576.26    7.42 9796.77    5.34  9901.5    -.11  9923.5  -11.11 10063.5  -17.11
 10113.5  -15.11 10163.5    -.2110343.39    2.31 10382.4    9.2710537.31   10.37
10568.94   14.2511252.12   16.5611693.84    33.611876.98   36.7412776.13   34.01
#Mann= 3 , 0 , 0
       0     .13       0  9901.5     .03       0 10163.5     .13       0
Bank Sta=9901.5,10163.5
XS Rating Curve= 0
Exp/Cntr=.3,.1

Type RM Length L Ch R = 1 ,101780.6,429.62,4264.66,524.86
BEGIN DESCRIPTION:
sj18p955
Bank Station offset =     13205
---- FLOW CHANGE LOCATION
END DESCRIPTION:
XS GIS Cut Line= 6
     3216228.616    13872697.242     3209888.667    13870218.269
     3209658.893    13869759.809     3206993.074    13869821.167
     3205183.676    13869634.908     3205022.626    13869745.269
#Sta/Elev= 30
       0   35.64  541.88    5.05  724.82    2.15 1322.66    2.59 1470.58    7.56
 1654.55    2.55 2558.62    1.17 6287.15    2.48 6741.43    8.74 6833.76    7.96
 6848.79    5.55 6849.77    1.99 6879.77  -12.01 7024.77  -18.01 7189.77  -16.51
 7199.77   -8.51 7233.77   -2.71    7262    6.06 7310.27   10.56 7523.52   11.91
 9041.55   12.32 9167.42   10.21  9197.9    2.45 9229.42     1.8 9610.37     1.4
 9785.17    9.95 10062.8    7.2210610.17   11.6911035.99   34.5612038.27   34.66
#Mann= 3 , 0 , 0
       0     .13       0 6849.77     .03       0 7233.77     .13       0
Bank Sta=6849.77,7233.77
XS Rating Curve= 0
Exp/Cntr=.3,.1